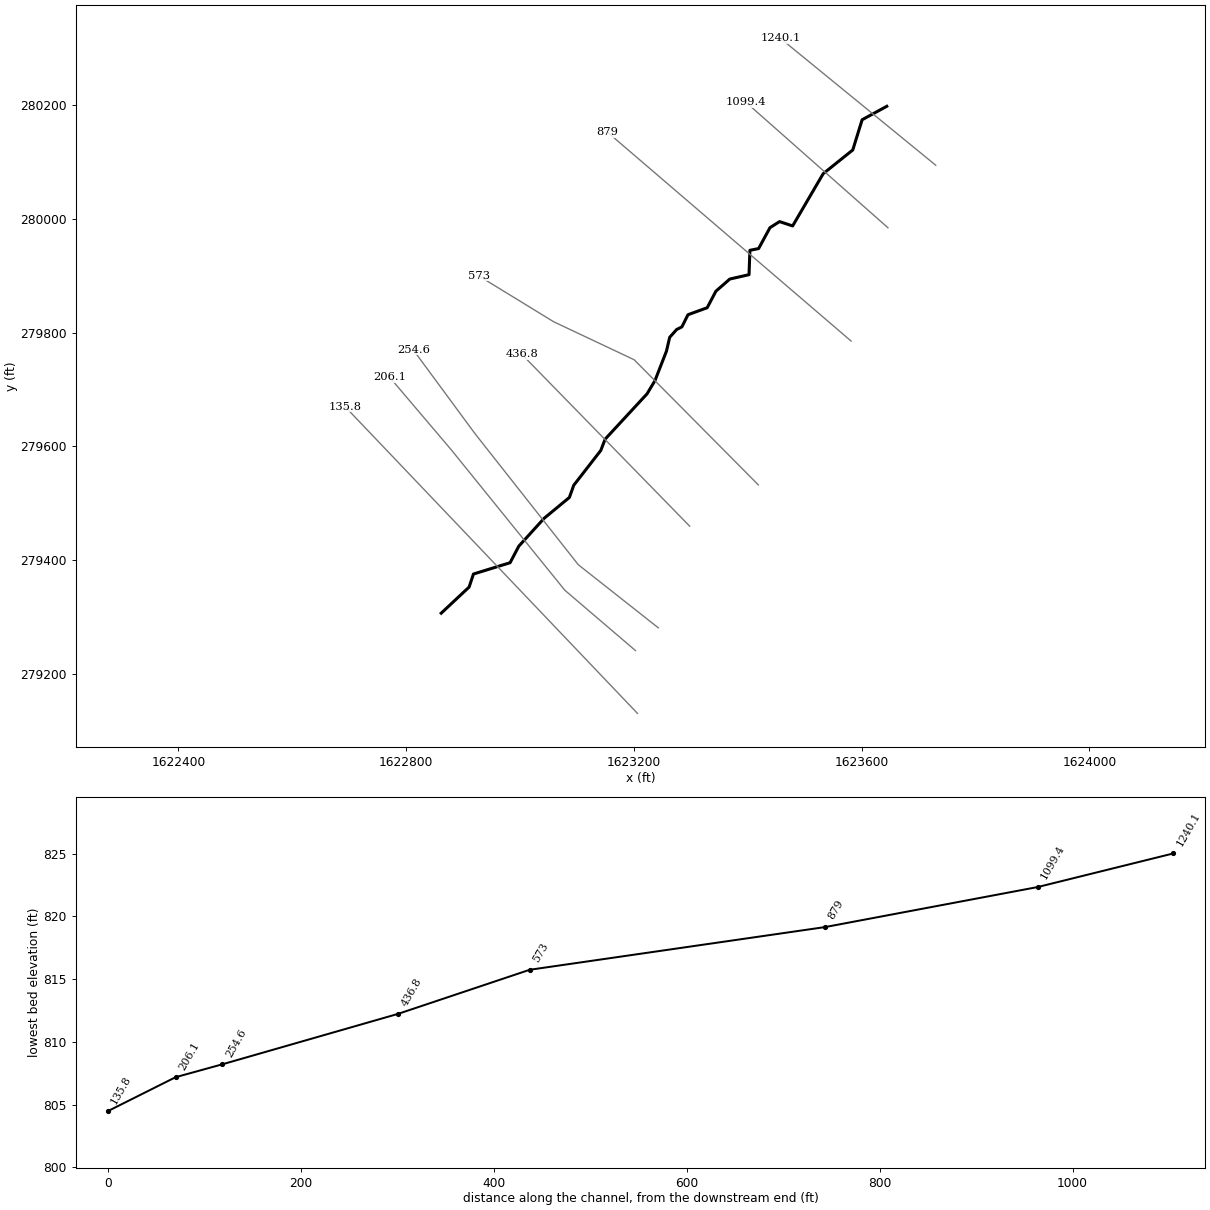
--- DOUGLSCPRN.prj (project) ---

Proj Title=DOUGLSCPRN
Current Plan=p01
Default Exp/Contr=0,0
English Units
Geom File=g01
Flow File=f01
Plan File=p01
BEGIN DESCRIPTION:
END DESCRIPTION:
DSS File=dss
DSS Export Rating Curves= 0
DSS Export Rating Curve Sorted= 0
DSS Export Volume Flow Curves= 0
DXF OffsetX= 0
DXF OffsetY= 0
DXF ScaleX= 0
DXF ScaleY= 0

--- DOUGLSCPRN.p01 (plan) ---

Plan Title=Floodplain
Program Version=4.10
Short Identifier=Floodplain
Geom File=g01
Flow File=f01
Subcritical Flow
K Sum by GR= 0
Std Step Tol= 0.01
Critical Tol= 0.01
Num of Std Step Trials= 20
Max Error Tol= 0.3
Flow Tol Ratio= 0.001
Split Flow NTrial= 30
Split Flow Tol= 0.02
Split Flow Ratio= 0.02
Log Output Level= 0
Friction Slope Method= 1
Unsteady Friction Slope Method= 2
Unsteady Bridges Friction Slope Method= 1
Parabolic Critical Depth
Global Vel Dist= 0 , 0 , 0
Global Log Level= 0
CheckData=True
Encroach Param=-1 ,0,0, 0
Run HTab= 0
Run UNet= 0
Run PostProcess= 0
Run WQNet= 0
UNET Theta= 0
UNET Theta Warmup= 0
UNET ZTol= 0
UNET ZSATol= 0
UNET MxIter= 0
UNET MaxInSteps= 0
UNET DtIC= 0
UNET DtMin= 0
UNET MaxCRTS= 0
UNET WFStab= 0
UNET SFStab= 0
UNET WFX= 1
UNET SFX= 1
UNET DSS MLevel= 1
UNET DZMax Abort= 0
UNET Convert EG Bridges= 0
UNET Use Existing IB Tables= 0
UNET Froude Reduction=False
UNET Froude Limit= 0
UNET Froude Power= 0
UNET Time Slicing=0,0, 5
UNET Junction Losses=0
DSS File=dss
Write IC File= 0
Write IC File at Sim End=0
Echo Input=False
Echo Parameters=False
Echo Output=False
Write Detailed= 0
WQ AD Non Conservative
WQ ULTIMATE=-1
WQ Max Comp Step=1HOUR
WQ Output Interval=15MIN
WQ Output Selected Increments= 0
WQ Output face flow=0
WQ Output face velocity=0
WQ Output face area=0
WQ Output face dispersion=0
WQ Output cell volume=0
WQ Output cell surface area=0
WQ Output cell continuity=0
WQ Output cumulative cell continuity=0
WQ Output face conc=0
WQ Output face dconc_dx=0
WQ Output face courant=0
WQ Output face peclet=0
WQ Output face adv mass=0
WQ Output face disp mass=0
WQ Output cell mass=0
WQ Output cell source sink temp=0
WQ Output cell source sink nsm=0
WQ Output MaxMinRange=-1
WQ Daily Max Min Mean=-1
WQ Daily Range=0
WQ Daily Time=0
WQ Create Restart=0
WQ Fixed Restart=0
WQ System Summary=0
WQ Use Fixed Temperature=0
Sorting and Armoring Iterations= 10
XS Update Threshold= 0.02
Hydraulics Update Threshold= 0.02
Energy Slope Method= 1
Volume Change Method= 0
XS Weighting Method= 0
Number of US Weighted Cross Sections= 1
Number of DS Weighted Cross Sections= 1
Upstream XS Weight=0.25
Main XS Weight=0.5
Downstream XS Weight=0.25
Number of DS XS's Weighted with US Boundary= 1
Upstream Boundary Weight= 1
Weight of XSs Associated with US Boundary= 0
Number of US XS's Weighted with DS Boundary= 1
Downstream Boundary Weight= 0.5
Weight of XSs Associated with DS Boundary= 0.5
Sediment Output Level= 4
Mass or Volume Output= 0
Output Increment Type= 1
Profile and TS Output Increment= 10
XS Output Flag= 0
XS Output Increment= 10
Disregard all LS=0
Disregard all Conn=0
Disregard all Breaches=0
Disregard all Pumps=0

--- DOUGLSCPRN.f01 (steady flow) ---

Flow Title=NFF Regression Equation
Program Version=4.10
Number of Profiles= 1
Profile Names=P100yr
River Rch & RM=DOUGLSCPRN,Main            ,1240.1
434.5291
River Rch & RM=DOUGLSCPRN,Main            ,573
447.6723
River Rch & RM=DOUGLSCPRN,Main            ,254.6
450.8567
Boundary for River Rch & Prof#=DOUGLSCPRN,Main            , 1
Up Type= 0
Dn Type= 3
Dn Slope=0.04113
DSS Import GetInterval= 0
DSS Import GetPeak= 0
DSS Import FillOption= 0

--- DOUGLSCPRN.g01 (geometry) ---

Geom Title=USGS 10m DEM
Program Version=4.10

River Reach=DOUGLSCPRN      ,Main
Reach XY= 30
     1623644.075      280198.427     1623600.806      280174.743
     1623584.387      280121.596     1623532.363      280079.736
     1623478.756      279987.838     1623455.781      279995.496
     1623438.933      279984.774     1623419.021      279948.015
     1623403.705      279944.952     1623402.174      279902.066
     1623368.478      279894.408     1623343.971      279872.965
     1623328.655      279843.864     1623294.959      279831.611
     1623284.238      279810.167     1623275.048      279805.573
     1623262.794      279791.788     1623257.164      279767.558
     1623236.916      279715.467     1623222.972      279692.231
     1623149.453      279612.586     1623141.795      279592.675
     1623094.314      279531.409     1623086.656      279509.967
     1623042.239      279473.207     1622997.821      279424.195
     1622982.505      279395.093     1622918.176      279375.182
     1622910.518      279352.208     1622861.505      279306.259

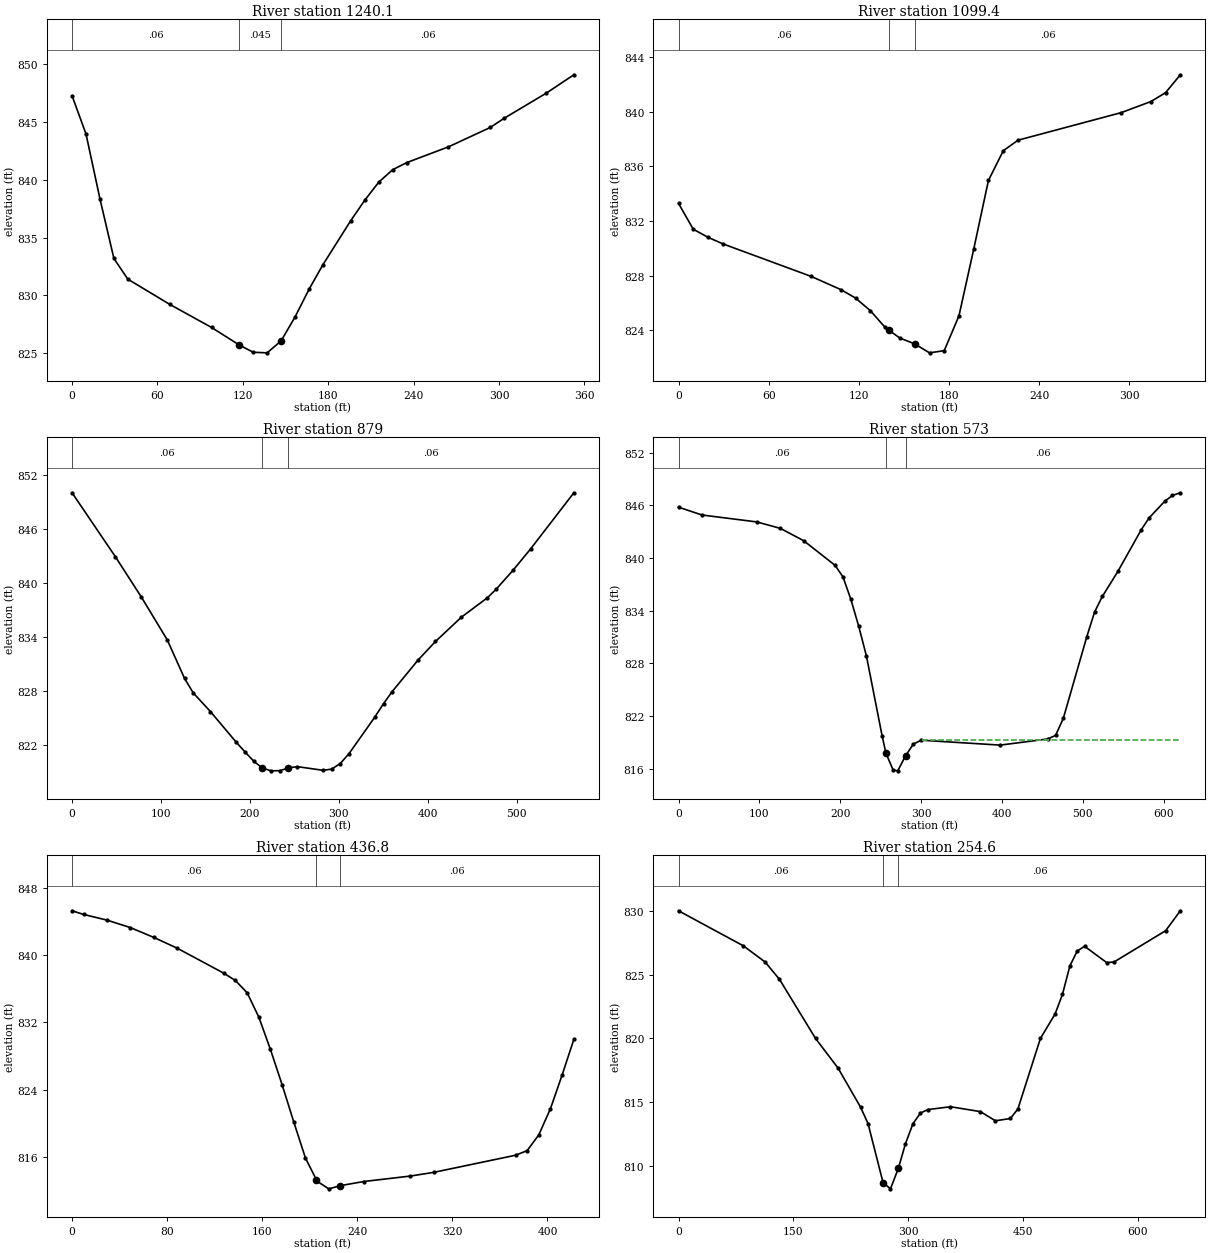
Type RM Length L Ch R = 1 ,1240.1  ,140.8,140.7,139.8
XS GIS Cut Line= 2
     1623730.133      280094.686     1623457.246      280318.051
#Sta/Elev= 24
       0  847.28     9.8  843.97    19.6  838.35    29.4  833.19    39.2   831.4
    68.6  829.22      98  827.22   117.6  825.69   127.3  825.07   137.1  825.02
   146.9  826.06   156.7  828.13   166.5  830.52   176.3  832.66   195.9  836.48
   205.7  838.24   215.5   839.8   225.3  840.88   235.1  841.49   264.5  842.86
   293.9  844.54   303.7  845.34   333.1   847.5   352.6   849.1
#Mann= 3 , 0 , 0
       0     .06       0   117.6    .045       0   146.9     .06       0
Bank Sta=117.6,146.9
XS Rating Curve= 0 ,0
Exp/Cntr=0.3,0.1

Type RM Length L Ch R = 1 ,1099.4  ,217,220.4,220.3
XS GIS Cut Line= 2
     1623646.192      279984.624     1623396.192      280205.979
#Sta/Elev= 23
       0  833.28     9.8  831.39    19.6   830.8    29.5  830.32    88.4  827.93
     108  826.97   117.8  826.35   127.7  825.42   137.5   824.2   140.1  823.99
   147.3  823.42   157.1     823     167  822.34   176.8   822.5   186.6  825.05
   196.4  829.92   206.2  834.96   216.1  837.14   225.9  837.91   294.6  839.93
   314.3  840.74   324.1  841.39   333.9   842.7
#Mann= 3 , 0 , 0
       0     .06       0   140.1    .045       0   157.1     .06       0
Bank Sta=140.1,157.1
XS Rating Curve= 0 ,0
Exp/Cntr=0.3,0.1

Type RM Length L Ch R = 1 ,879     ,307.7,306,319.3
XS GIS Cut Line= 2
     1623581.456      279785.223     1623153.246      280153.101
#Sta/Elev= 30
       0     850    48.7  842.91    77.9  838.44   107.1  833.68   126.5  829.41
   136.3   827.8   155.7  825.72   184.9   822.3   194.7  821.23   204.4  820.22
   214.1  819.46   223.9  819.15   233.6  819.17   243.3  819.46   253.1  819.62
   282.3  819.21     292  819.34   301.7  819.96   311.5  821.05   340.7  825.13
   350.4  826.61   360.1  827.94   389.3  831.45   408.8   833.5     438   836.2
   467.2  838.35   476.9  839.28   496.4  841.44   515.9  843.78   564.5     850
#Mann= 3 , 0 , 0
       0     .06       0   214.1    .045       0   243.3     .06       0
Bank Sta=214.1,243.3
XS Rating Curve= 0 ,0
Exp/Cntr=0.3,0.1

Type RM Length L Ch R = 1 ,573     ,136.8,136.3,136.4
XS GIS Cut Line= 4
     1623418.452       279532.14     1623200.388      279752.355
     1623058.952       279819.26     1622927.442      279899.989
#Sta/Elev= 30
       0  845.78      29  844.89    96.8   844.1   125.9  843.37     155  841.95
   193.7  839.15   203.4  837.84   213.1   835.3   222.8  832.24   232.4  828.84
   251.8  819.74  256.57  817.75   265.5  815.84   271.2  815.75   280.9  817.48
   290.5   818.8   300.2  819.24   397.9  818.68   456.6  819.38   466.4  819.79
     476  821.74     505  831.02   514.6  833.83   524.2  835.61   543.5  838.47
   572.5  843.23   582.1  844.56   601.4  846.45     611  847.12   620.7  847.42
#Mann= 3 , 0 , 0
       0     .06       0  256.57    .045       0   280.9     .06       0
#XS Ineff= 2 , 0
                          301.69          819.29
Permanent Ineff=
       F       F
Bank Sta=256.57,280.9
XS Rating Curve= 0 ,0
Exp/Cntr=0.3,0.1

Type RM Length L Ch R = 1 ,436.8   ,184,182.2,179.7
XS GIS Cut Line= 2
     1623297.884      279459.451     1623003.232      279761.783
#Sta/Elev= 27
       0  845.27     9.8  844.83    29.4  844.16    49.1  843.27    68.7  842.11
    88.4  840.83   127.6  837.86   137.4  836.99   147.3  835.53   157.1  832.65
   166.9   828.8   176.7  824.62   186.5   820.2   196.4  815.88   205.5  813.34
   206.2  813.14     216  812.24   225.8  812.62   245.4  813.11   284.7  813.76
   304.4   814.2   373.1  816.23   382.9  816.78   392.7  818.65   402.5  821.76
   412.4  825.79   422.2     830
#Mann= 3 , 0 , 0
       0     .06       0   205.5    .045       0   225.8     .06       0
Bank Sta=205.5,225.8
XS Rating Curve= 0 ,0
Exp/Cntr=0.3,0.1

Type RM Length L Ch R = 1 ,254.6   ,48.2,48.5,48.8
XS GIS Cut Line= 4
     1623242.805      279280.528     1623102.346      279391.527
     1622920.738      279622.426     1622812.472       279769.72
#Sta/Elev= 30
       0     830    84.8  827.25   113.1  825.99   131.9  824.63     179     820
   208.4  817.68   237.8  814.62   247.6  813.33   267.2  808.71   276.9  808.22
   287.3  809.84   296.5  811.76   306.3  813.32   316.1  814.16   325.9  814.43
   355.3  814.65   394.4  814.27     414  813.55   433.6  813.73   443.4  814.48
   472.8     820     492  821.92   501.6  823.45   511.3  825.68   520.9  826.85
   530.5  827.22   559.4  825.94     569  825.99   636.4  828.44   655.6     830
#Mann= 3 , 0 , 0
       0     .06       0   267.2    .045       0   287.3     .06       0
Bank Sta=267.2,287.3
XS Rating Curve= 0 ,0
Exp/Cntr=0.3,0.1

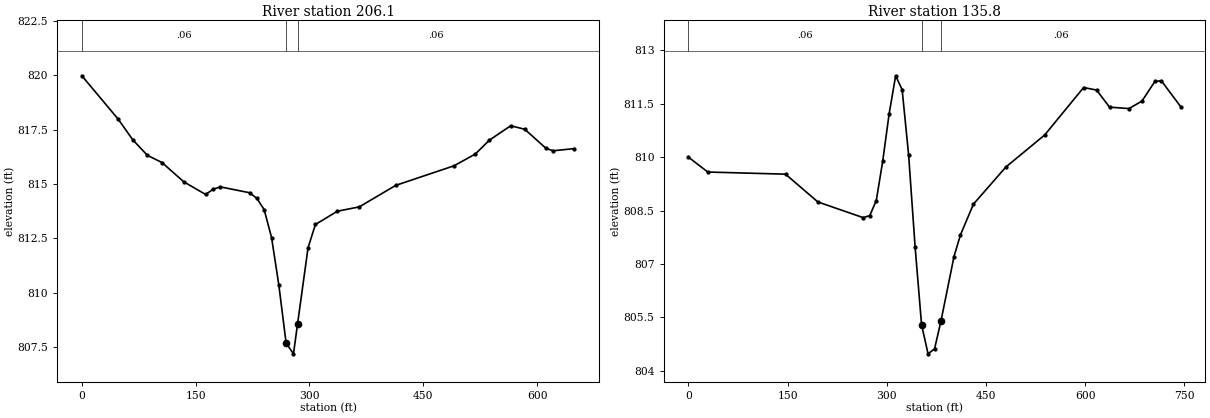
Type RM Length L Ch R = 1 ,206.1   ,68.6,70.4,72.1
XS GIS Cut Line= 4
      1623202.74      279240.463       1623078.7      279346.604
     1622879.047      279593.999     1622770.541      279722.038
#Sta/Elev= 30
       0  819.98      48  817.98    67.2  817.03    86.4  816.32   105.6  815.99
   134.4   815.1   163.2  814.52   172.9  814.76   182.5  814.87     221   814.6
   230.7  814.34   240.3  813.82     250  812.54   259.6  810.35   269.2  807.68
   278.9  807.19   284.2  808.55   298.1  812.07   307.8  813.14   336.7  813.75
   365.6  813.95   413.7  814.94   490.5  815.84   518.5  816.38   537.1  817.02
   565.1  817.68   583.7  817.52   611.7  816.64     621  816.53     649  816.63
#Mann= 3 , 0 , 0
       0     .06       0   269.2    .045       0   284.2     .06       0
Bank Sta=269.2,284.2
XS Rating Curve= 0 ,0
Exp/Cntr=0.3,0.1

Type RM Length L Ch R = 1 ,135.8   ,136.5,135.8,134.9
XS GIS Cut Line= 2
     1623206.168      279129.924     1622693.123      279669.329
#Sta/Elev= 30
       0     810    29.4  809.58   146.9  809.52   195.9  808.74   264.5   808.3
   274.3  808.36   284.1  808.78   293.8  809.88   303.6  811.22   313.4  812.28
   323.2  811.89     333  810.06   342.8  807.48   352.6  805.29   362.4  804.48
   372.2  804.62     382  805.41   401.6  807.21   411.4  807.82     431  808.68
     480  809.72   538.7  810.62   597.5  811.95   617.1  811.88   636.7   811.4
   666.1  811.36   685.7  811.57   705.2  812.12     715  812.14   744.4  811.41
#Mann= 3 , 0 , 0
       0     .06       0   352.6    .045       0     382     .06       0
Bank Sta=352.6,382
XS Rating Curve= 0 ,0
Exp/Cntr=0.3,0.1

Chan Stop Cuts=-1
Use User Specified Reach Order=0
Composite Channel Slope=5